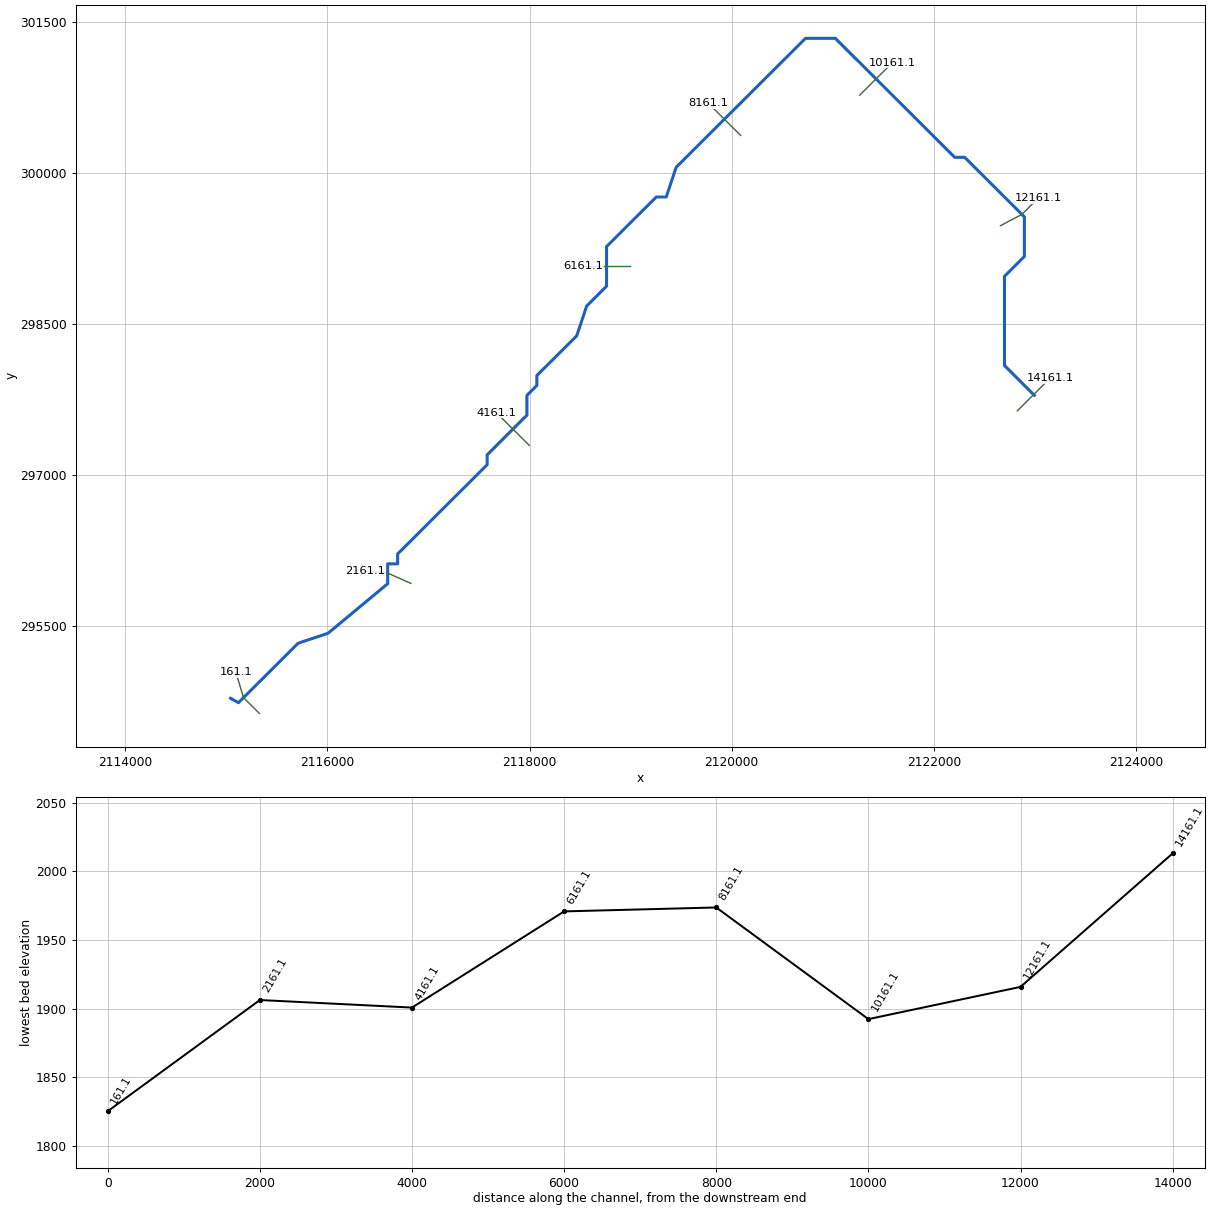
--- MlgnCkT2.prj (project) ---

Proj Title=MlgnCkT2
Current Plan=p01
Geom File=g01
Flow File=f01
Plan File=p01
DSS Export Rating Curves=0
DSS Export Rating Curve Sorted=0
DSS Export Volume Flow Curves=0
DXF OffsetX=0
DXF OffsetY=0
DXF ScaleX=0
DXF ScaleY=0

--- MlgnCkT2.p01 (plan) ---

Plan Title=Floodplain
Program Version=4.00
Geom File=g01
Flow File=f01
K Sum by GR=0
Std Step Tol=0.01
Critical Tol=0.01
Num of Std Step Trials=20
Max Error Tol=0.3
Flow Tol Ratio=0.001
Split Flow NTrial=30
Split Flow Tol=0.02
Split Flow Ratio=0.02
Log Output Level=0
Friction Slope Method=1
Unsteady Friction Slope Method=2
Unsteady Bridges Friction Slope Method=1
Global Log Level=0
CheckData=False
Run HTab=0
Run UNet=0
Run PostProcess=0
UNET Theta=0
UNET Theta Warmup=0
UNET ZTol=0
UNET ZSATol=0
UNET MxIter=0
UNET MaxInSteps=0
UNET DtIC=0
UNET DtMin=0
UNET MaxCRTS=0
UNET WFStab=0
UNET SFStab=0
UNET WFX=0
UNET SFX=0
UNET DSS MLevel=0
UNET DZMax Abort=0
UNET Convert EG Bridges=0
UNET Use Existing IB Tables=0
UNET Froude Limit=0
UNET Froude Power=0
Write IC File=0
Echo Input=False
Echo Output=False
Write Detailed=0

--- MlgnCkT2.f01 (steady flow) ---

Flow Title=USGS Regression (Report 2010-5033)
Program Version=4.00
Number of Profiles=1
Profile Names=P100yr
River Rch & RM=MlgnCkT2,Main      ,14161.1
521.2398
River Rch & RM=MlgnCkT2,Main      ,12161.1
521.2398
River Rch & RM=MlgnCkT2,Main      ,12161.1
598.3089
River Rch & RM=MlgnCkT2,Main      ,12161.1
616.1918
River Rch & RM=MlgnCkT2,Main      ,10161.1
873.2227
River Rch & RM=MlgnCkT2,Main      ,10161.1
898.5345
River Rch & RM=MlgnCkT2,Main      ,8161.1
1200.273
River Rch & RM=MlgnCkT2,Main      ,6161.1
1246.970
Boundary for River Rch & Prof#=MlgnCkT2,Main      ,1
Up Type=0
Dn Type=3
Dn Slope=0.023916

--- MlgnCkT2.g01 (geometry) ---

Geom Title=USGS 1/9 Arc Second
Program Version=4.00

River Reach=MlgnCkT2     ,Main
Reach XY= 30
     2122994.163      297790.429     2122698.891      298085.701
     2122698.891      298971.517     2122895.739      299168.365
     2122895.739      299562.061     2122305.195      300152.605
     2122206.771      300152.605     2121025.683      301333.693
     2120730.411      301333.693     2119450.899      300054.181
     2119352.475      299758.909     2119254.051      299758.909
     2118761.931      299266.789     2118761.931      298873.093
     2118565.083      298676.245     2118466.659      298380.973
     2118072.963      297987.277     2118072.963      297888.853
     2117974.539      297790.429     2117974.539      297593.581
     2117580.843      297199.885     2117580.843      297101.461
     2116695.027      296215.645     2116695.027      296117.221
     2116596.603      296117.221     2116596.603      295920.373
     2116006.059      295428.253     2115710.787      295329.829
     2115120.243      294739.285     2115041.615      294783.089

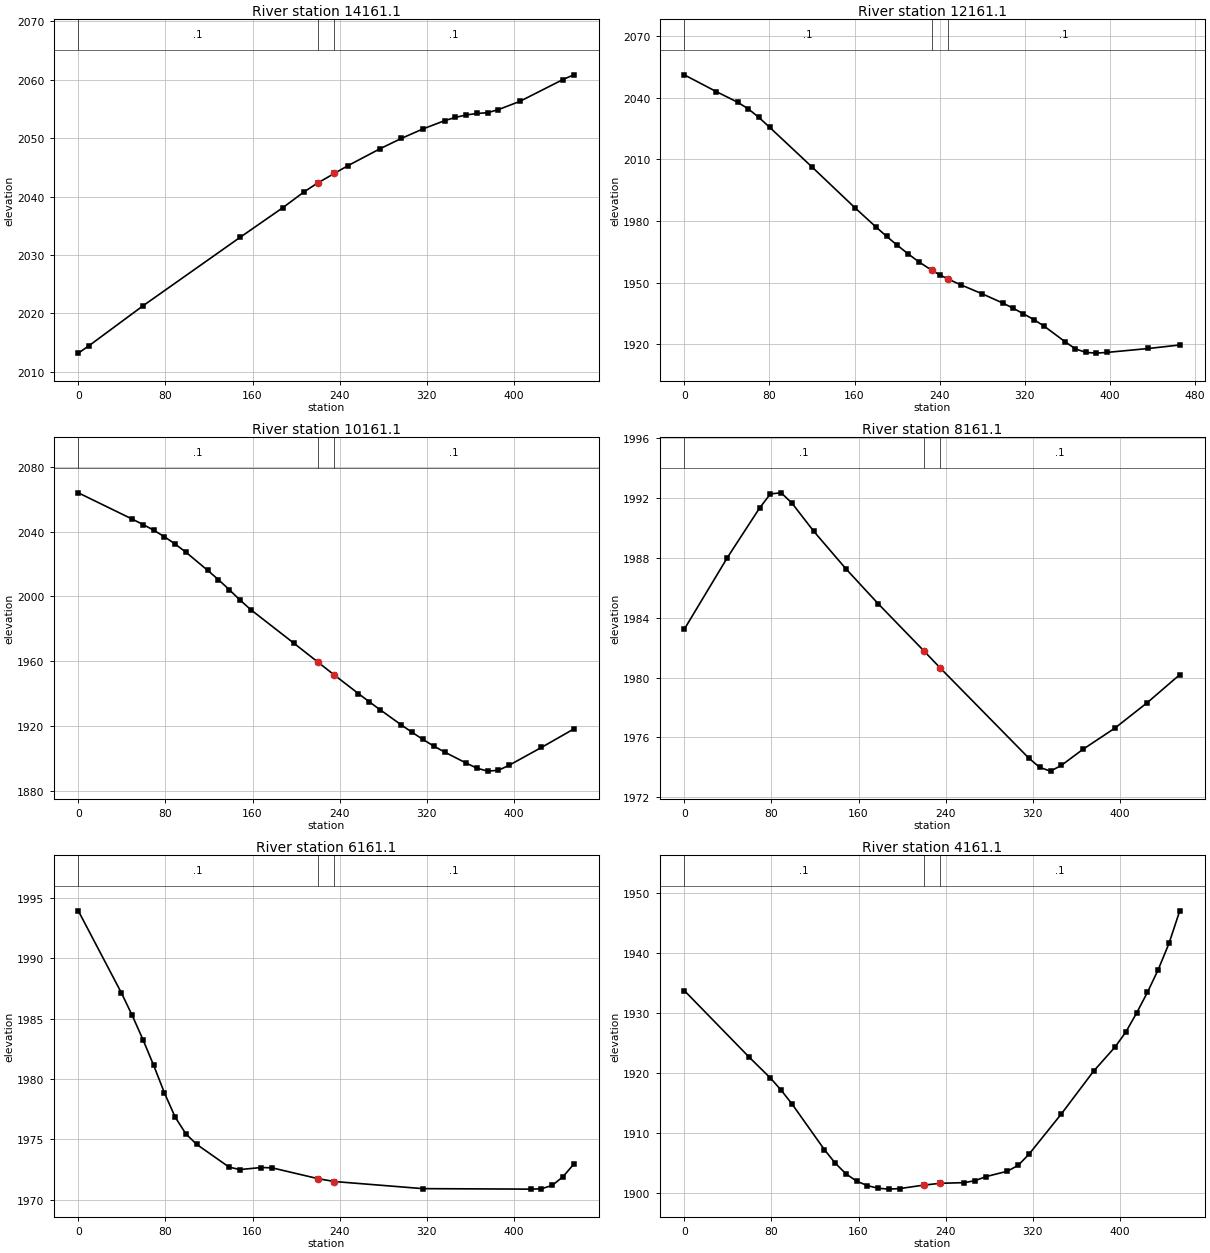
Type RM Length L Ch R = 1 ,14161.1,2006.9,2000,2000
XS GIS Cut Line= 3
     2122826.225      297636.634     2122987.092      297797.500
     2123147.959      297958.367
#Sta/Elev= 21
       0 2013.19     9.9 2014.47    59.4 2021.29   148.4 2032.99   187.9 2038.10
   207.7 2040.85     220 2042.33     235 2043.94   247.3 2045.25   277.0 2048.17
   296.7 2049.95   316.5 2051.57   336.3 2052.98   346.2 2053.54   356.1 2053.96
   366.0 2054.21   375.9 2054.35   385.8 2054.88   405.5 2056.29   445.1 2060.03
   455.0 2060.83
#Mann= 3 , 0 , 0
       0     0.1       0     220   0.045       0     235     0.1       0
Bank Sta=     220,     235
Exp/Cntr=0.3,0.1

Type RM Length L Ch R = 1 ,12161.1,1993.1,2000,2000
XS GIS Cut Line= 3
     2122658.918      299474.095     2122871.326      299586.474
     2123030.595      299745.743
#Sta/Elev= 30
       0 2051.05    30.0 2042.92    50.1 2037.74    60.1 2034.52    70.1 2030.35
    80.1 2025.61   120.2 2006.18   160.2 1986.53   180.2 1977.07   190.2 1972.52
   200.2 1968.19   210.3 1964.07   220.3 1960.20   232.8 1955.99   240.3 1953.75
   247.8 1951.82   259.9 1948.98   279.5 1944.73   299.1 1940.18   308.9 1937.66
   318.6 1934.95   328.4 1932.12   338.2 1928.90   357.8 1921.34   367.6 1917.86
   377.4 1916.15   387.2 1915.80   397.0 1916.14   436.2 1918.05   465.6 1919.76
#Mann= 3 , 0 , 0
       0     0.1       0   232.8   0.045       0   247.8     0.1       0
Bank Sta=   232.8,   247.8
Exp/Cntr=0.3,0.1

Type RM Length L Ch R = 1 ,10161.1,1962.7,2000,2037.3
XS GIS Cut Line= 3
     2121267.418      300770.225     2121428.285      300931.092
     2121589.151      301091.958
#Sta/Elev= 30
       0 2063.90    49.5 2047.70    59.4 2044.36    69.2 2040.88    79.1 2036.82
    89.0 2032.26    98.9 2027.24   118.7 2016.14   128.6 2010.40   138.5 2004.24
   148.4 1997.85   158.3 1991.89   197.8 1971.24     220 1959.52     235 1951.59
   257.2 1940.10   267.1 1935.08   277.0 1930.21   296.7 1920.74   306.6 1916.17
   316.5 1911.80   326.4 1907.73   336.3 1904.06   356.1 1897.27   366.0 1894.11
   375.9 1892.28   385.8 1892.81   395.6 1895.89   425.3 1906.88   455.0 1918.27
#Mann= 3 , 0 , 0
       0     0.1       0     220   0.045       0     235     0.1       0
Bank Sta=     220,     235
Exp/Cntr=0.3,0.1

Type RM Length L Ch R = 1 ,8161.1,1983.2,2000,2010.9
XS GIS Cut Line= 3
     2120088.455      300370.004     2119927.588      300530.870
     2119766.721      300691.737
#Sta/Elev= 19
       0 1983.22    39.6 1988.01    69.2 1991.32    79.1 1992.26    89.0 1992.33
    98.9 1991.64   118.7 1989.78   148.4 1987.26   178.0 1984.93     220 1981.78
     235 1980.64   316.5 1974.61   326.4 1974.00   336.3 1973.75   346.2 1974.13
   366.0 1975.20   395.6 1976.63   425.3 1978.33   455.0 1980.19
#Mann= 3 , 0 , 0
       0     0.1       0     220   0.045       0     235     0.1       0
Bank Sta=     220,     235
Exp/Cntr=0.3,0.1

Type RM Length L Ch R = 1 ,6161.1,2018.6,2000,1981.4
XS GIS Cut Line= 3
     2118989.431      299071.357     2118761.931      299071.357
     2118534.431      299071.357
#Sta/Elev= 21
       0 1993.92    39.6 1987.12    49.5 1985.26    59.4 1983.25    69.2 1981.13
    79.1 1978.84    89.0 1976.83    98.9 1975.44   108.8 1974.58   138.5 1972.70
   148.4 1972.50   168.2 1972.67   178.0 1972.64     220 1971.75     235 1971.51
   316.5 1970.92   415.4 1970.88   425.3 1970.91   435.2 1971.19   445.1 1971.91
   455.0 1972.95
#Mann= 3 , 0 , 0
       0     0.1       0     220   0.045       0     235     0.1       0
Bank Sta=     220,     235
Exp/Cntr=0.3,0.1

Type RM Length L Ch R = 1 ,4161.1,1985.5,2000,2010.8
XS GIS Cut Line= 3
     2117996.759      297294.068     2117835.892      297454.935
     2117675.025      297615.801
#Sta/Elev= 30
       0 1933.76    59.4 1922.71    79.1 1919.20    89.0 1917.17    98.9 1914.89
   128.6 1907.30   138.5 1905.06   148.4 1903.26   158.3 1902.04   168.2 1901.29
   178.0 1900.86   187.9 1900.71   197.8 1900.80     220 1901.38     235 1901.68
   257.2 1901.79   267.1 1902.12   277.0 1902.79   296.7 1903.69   306.6 1904.67
   316.5 1906.51   346.2 1913.21   375.9 1920.35   395.6 1924.37   405.5 1926.86
   415.4 1930.03   425.3 1933.46   435.2 1937.24   445.1 1941.60   455.0 1947.03
#Mann= 3 , 0 , 0
       0     0.1       0     220   0.045       0     235     0.1       0
Bank Sta=     220,     235
Exp/Cntr=0.3,0.1

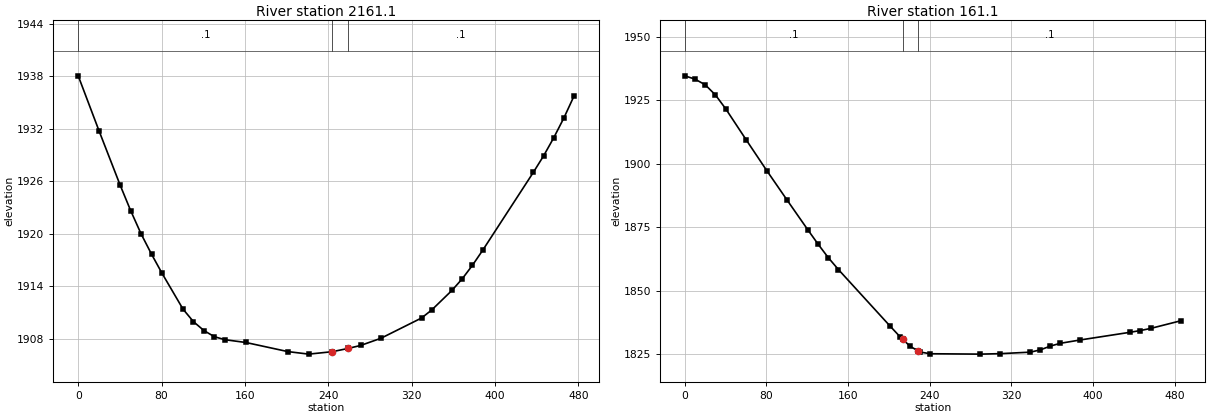
Type RM Length L Ch R = 1 ,2161.1,2008.6,2000,1971.3
XS GIS Cut Line= 3
     2116826.221      295923.550     2116596.603      296025.920
     2116373.145      296045.910
#Sta/Elev= 30
       0 1938.05    20.1 1931.72    40.2 1925.56    50.3 1922.64    60.3 1919.98
    70.4 1917.64    80.4 1915.47   100.6 1911.36   110.6 1909.93   120.7 1908.91
   130.7 1908.21   140.8 1907.87   160.9 1907.55   201.1 1906.51   221.2 1906.22
   243.9 1906.50   258.9 1906.87   270.9 1907.21   290.4 1908.03   329.4 1910.35
   339.2 1911.27   358.7 1913.52   368.5 1914.84   378.2 1916.37   388.0 1918.08
   436.7 1927.01   446.5 1928.89   456.2 1930.95   466.0 1933.23   475.8 1935.76
#Mann= 3 , 0 , 0
       0     0.1       0   243.9   0.045       0   258.9     0.1       0
Bank Sta=   243.9,   258.9
Exp/Cntr=0.3,0.1

Type RM Length L Ch R = 1 ,161.1,192.8,161.1,139.2
XS GIS Cut Line= 3
     2115326.760      294633.360     2115170.539      294789.582
     2115094.058      295043.021
#Sta/Elev= 30
       0 1934.60    10.0 1933.31    20.1 1931.06    30.1 1927.06    40.2 1921.58
    60.2 1909.40    80.3 1897.33   100.4 1885.62   120.5 1874.04   130.6 1868.36
   140.6 1863.04   150.6 1858.33   200.8 1836.25   210.9 1831.91   213.4 1830.96
   220.9 1828.11   228.4 1826.42   230.7 1825.89   240.5 1825.23   289.6 1825.08
   309.2 1825.27   338.6 1825.86   348.4 1826.77   358.2 1828.26   368.0 1829.35
   387.6 1830.67   436.6 1833.70   446.4 1834.37   456.2 1835.18   485.7 1838.19
#Mann= 3 , 0 , 0
       0     0.1       0   213.4   0.045       0   228.4     0.1       0
Bank Sta=   213.4,   228.4
Exp/Cntr=0.3,0.1